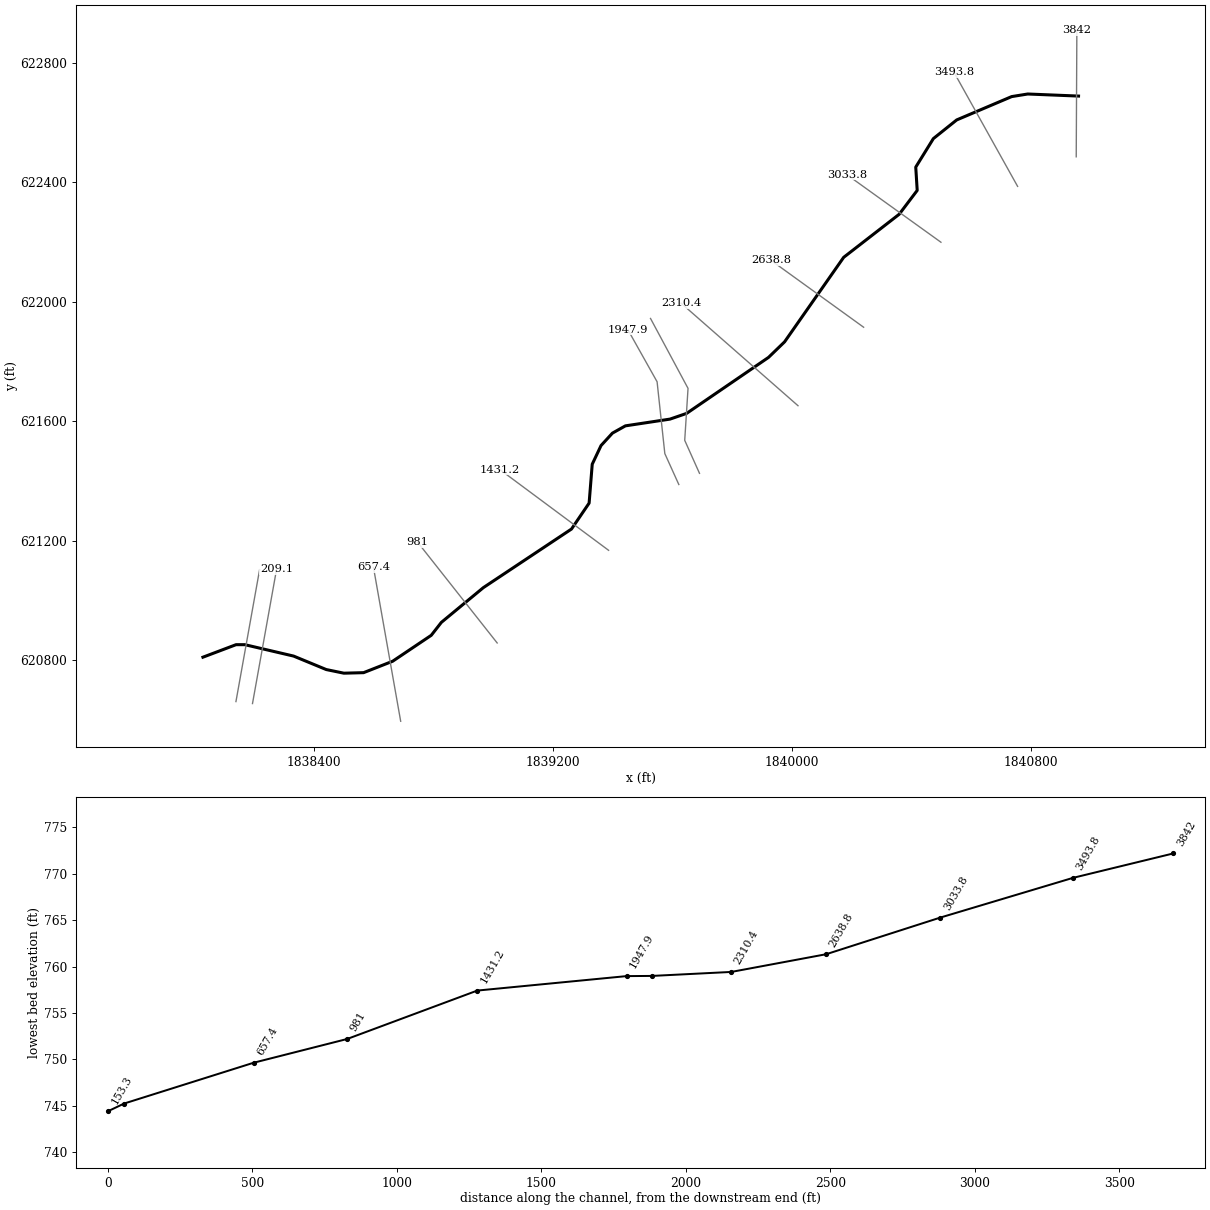
--- CabbageFrk.prj (project) ---

Proj Title=CabbageFrk
Current Plan=p01
Default Exp/Contr=0,0
English Units
Geom File=g01
Flow File=f01
Plan File=p01
BEGIN DESCRIPTION:
AMEC Environment & Infrastructure, 2013
Projection: NAD 1983 State Plane West Virginia South FIPS 4702 (US Feet)
Vertical Datum: NAVD 1988
END DESCRIPTION:
DSS Export Rating Curves= 0
DSS Export Rating Curve Sorted= 0
DSS Export Volume Flow Curves= 0
DXF OffsetX= 0
DXF OffsetY= 0
DXF ScaleX= 0
DXF ScaleY= 0

--- CabbageFrk.p01 (plan) ---

Plan Title=Floodplain
Program Version=4.00
Geom File=g01
Flow File=f01
K Sum by GR=0
Std Step Tol=0.01
Critical Tol=0.01
Num of Std Step Trials=20
Max Error Tol=0.3
Flow Tol Ratio=0.001
Split Flow NTrial=30
Split Flow Tol=0.02
Split Flow Ratio=0.02
Log Output Level=0
Friction Slope Method=1
Unsteady Friction Slope Method=2
Unsteady Bridges Friction Slope Method=1
Global Log Level=0
CheckData=False
Run HTab=0
Run UNet=0
Run PostProcess=0
UNET Theta=0
UNET Theta Warmup=0
UNET ZTol=0
UNET ZSATol=0
UNET MxIter=0
UNET MaxInSteps=0
UNET DtIC=0
UNET DtMin=0
UNET MaxCRTS=0
UNET WFStab=0
UNET SFStab=0
UNET WFX=0
UNET SFX=0
UNET DSS MLevel=0
UNET DZMax Abort=0
UNET Convert EG Bridges=0
UNET Use Existing IB Tables=0
UNET Froude Limit=0
UNET Froude Power=0
Write IC File=0
Echo Input=False
Echo Output=False
Write Detailed=0

--- CabbageFrk.f01 (steady flow) ---

Flow Title=NFF Regression Equation
Program Version=4.00
Number of Profiles=1
Profile Names=P100yr
River Rch & RM=CabbageFrk,Main      ,3842
944.7448
River Rch & RM=CabbageFrk,Main      ,209.1
1046.799
River Rch & RM=CabbageFrk,Main      ,209.1
1044.030
Boundary for River Rch & Prof#=CabbageFrk,Main      ,1
Up Type=0
Dn Type=3
Dn Slope=0.010848

--- CabbageFrk.g01 (geometry) ---

Geom Title=USGS 3m DEM
Program Version=4.10

River Reach=CabbageFrk      ,Main
Reach XY= 30
     1840960.174      622688.927     1840789.975      622695.865
     1840736.138      622687.178      1840552.05      622609.015
     1840473.902      622546.489     1840414.858      622450.966
     1840419.748       622372.95     1840359.292      622292.922
     1840173.472      622148.764     1839975.502      621865.668
     1839921.667      621813.564     1839647.276      621625.983
     1839591.703      621606.876     1839442.346       621584.29
      1839398.93      621559.974     1839360.724       621518.29
     1839331.204      621455.767     1839320.791      621325.513
     1839261.747      621238.674     1838966.517      621042.408
     1838825.849       620926.04     1838791.973      620882.673
     1838662.606      620795.778     1838565.352      620757.565
     1838499.357      620755.824     1838440.308      620767.978
     1838330.892      620813.126     1838167.639      620851.325
     1838138.115      620851.323     1838027.141      620809.367

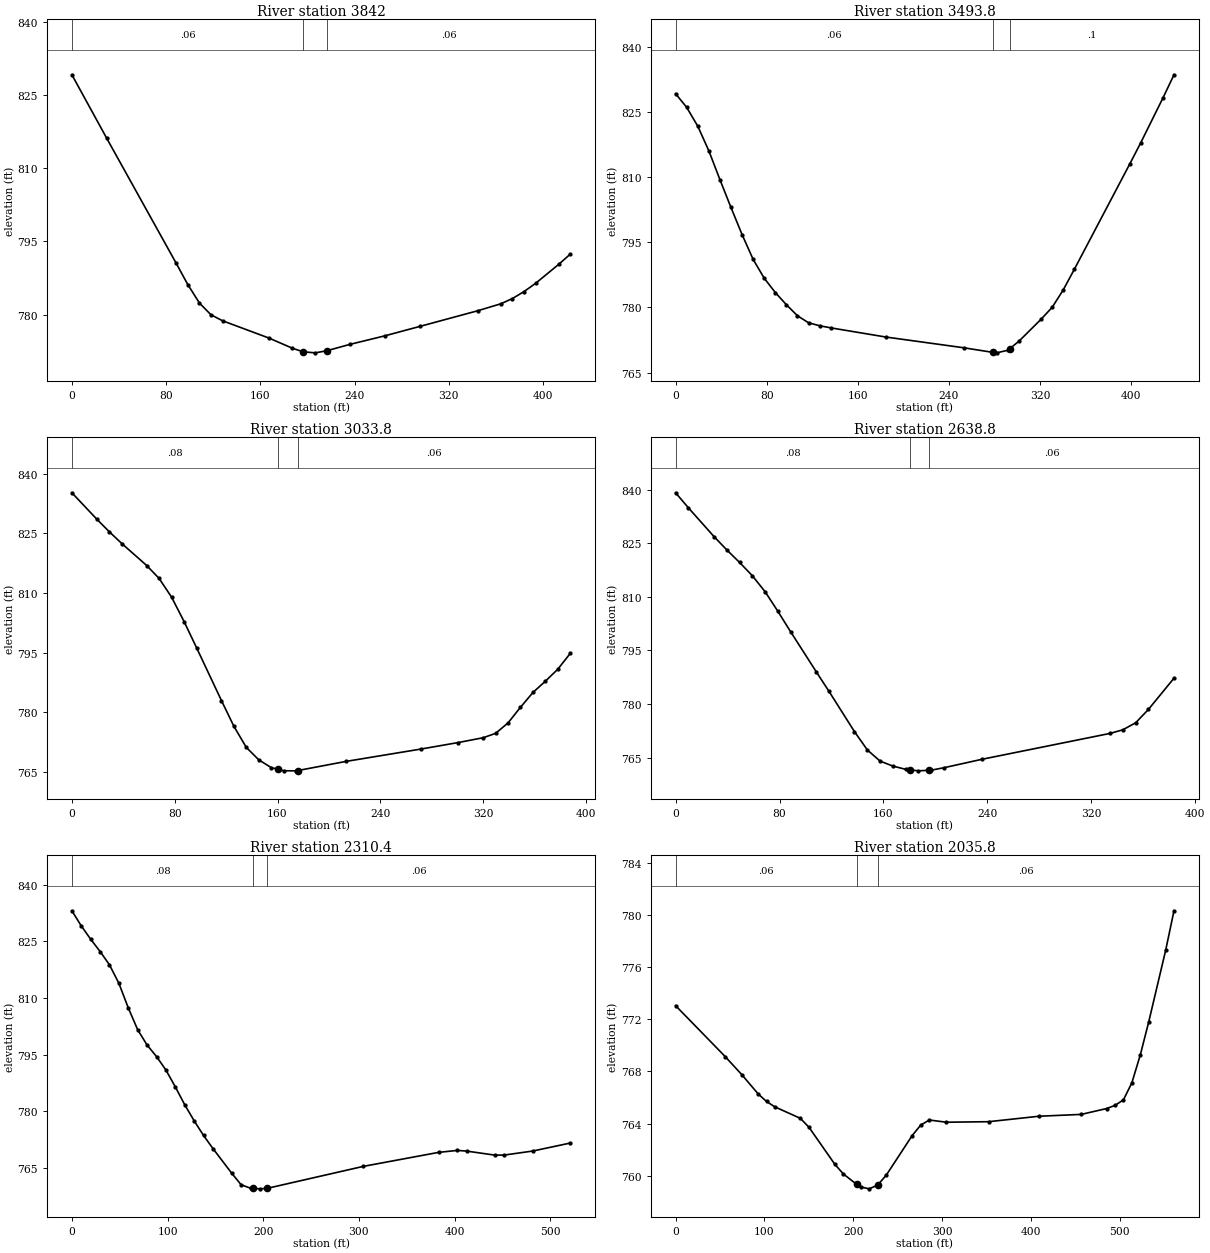
Type RM Length L Ch R = 1 ,3842    ,336.5,348.1,359.7
XS GIS Cut Line= 2
     1840952.415      622485.479     1840954.529       622908.69
#Sta/Elev= 22
       0  829.14    29.5  816.17    88.6  790.53    98.4  786.19   108.3   782.4
   118.1  779.99     128  778.76   167.3  775.23     187  773.17   196.3  772.41
   206.7   772.2   216.5  772.63   236.2  773.94   265.7  775.68   295.3   777.6
   344.5  780.81   364.2  782.24     374  783.31   383.8  784.72   393.7  786.42
   413.4  790.32   423.2  792.41
#Mann= 3 , 0 , 0
       0     .06       0   196.3    .045       0   216.5     .06       0
Bank Sta=196.3,216.5
XS Rating Curve= 0 ,0
Exp/Cntr=0.3,0.1

Type RM Length L Ch R = 1 ,3493.8  ,449.1,458.9,468.6
XS GIS Cut Line= 2
     1840756.054      622386.459     1840542.809      622768.811
#Sta/Elev= 30
       0  829.15     9.7  826.01    19.5  821.66    29.2     816    38.9   809.4
    48.6     803    58.4  796.74    68.1  791.05    77.8  786.73    87.6  783.42
    97.3  780.63     107  778.09   116.8  776.47   126.5  775.79   136.2  775.31
   184.8  773.19     253  770.73   278.4  769.68   282.1  769.56   291.9  770.16
   293.4  770.48   301.6  772.24     321  777.27   330.8  780.03   340.5  784.03
   350.2  788.74   398.9  812.96   408.6  817.87   428.1  828.17   437.8   833.5
#Mann= 3 , 0 , 0
       0     .06       0   278.4    .045       0   293.4      .1       0
Bank Sta=278.4,293.4
XS Rating Curve= 0 ,0
Exp/Cntr=0.3,0.1

Type RM Length L Ch R = 1 ,3033.8  ,429.9,394.9,428.3
XS GIS Cut Line= 2
     1840499.281      622199.327     1840184.278      622425.581
#Sta/Elev= 29
       0  835.17    19.4  828.53    29.1  825.38    38.8  822.42    58.2  816.89
    67.9  813.63    77.6  808.92    87.3   802.8      97  796.23   116.4  782.93
     126  776.51   135.7  771.18   145.4  768.05   155.1   766.1   160.7  765.64
   164.8   765.3   174.5  765.28   175.7  765.35   213.3  767.65   271.5  770.75
   300.6  772.39     320   773.6   329.7   774.7   339.4  777.33     349  781.23
   358.8  784.99   368.4   787.8   378.1  790.82   387.8   794.8
#Mann= 3 , 0 , 0
       0     .08       0   160.7    .045       0   175.7     .06       0
Bank Sta=160.7,175.7
XS Rating Curve= 0 ,0
Exp/Cntr=0.3,0.1

Type RM Length L Ch R = 1 ,2638.8  ,330.4,328.4,326.7
XS GIS Cut Line= 2
     1840240.256      621914.633     1839929.192      622139.264
#Sta/Elev= 27
       0  839.09     9.8   834.9    29.5  826.86    39.4  823.12    49.2  819.62
      59  815.92    68.9  811.42    78.7  805.96    88.5  800.25   108.2  789.08
   118.1  783.55   137.7  772.29   147.6  767.18   157.4  764.06   167.2  762.67
   177.1  761.75   180.2  761.62   186.9  761.33   195.2  761.49   196.8  761.52
   206.6   762.2   236.1  764.58   334.5   771.8   344.3   772.8   354.2  774.77
     364   778.5   383.7  787.24
#Mann= 3 , 0 , 0
       0     .08       0   180.2    .045       0   195.2     .06       0
Bank Sta=180.2,195.2
XS Rating Curve= 0 ,0
Exp/Cntr=0.3,0.1

Type RM Length L Ch R = 1 ,2310.4  ,295.9,274.6,252.2
XS GIS Cut Line= 2
     1840020.449      621651.794     1839628.774      621995.204
#Sta/Elev= 30
       0  833.14     9.8  829.13    19.7  825.57    29.5  822.34    39.3   818.8
    49.1  813.92      59  807.35    68.8  801.58    78.6  797.54    88.5  794.48
    98.3  790.91   108.1  786.45   117.9  781.73   127.8  777.45   137.6  773.57
   147.4  770.11   167.1  763.54   176.9   760.5   186.7  759.59   189.3  759.55
   196.6  759.42   204.3  759.56   304.7  765.38   383.3  769.09     403  769.61
   412.8  769.42   442.3  768.35   452.1  768.38   481.6  769.44   520.9  771.56
#Mann= 3 , 0 , 0
       0     .08       0   189.3    .045       0   204.3     .06       0
Bank Sta=189.3,204.3
XS Rating Curve= 0 ,0
Exp/Cntr=0.3,0.1

Type RM Length L Ch R = 1 ,2035.8  ,83.5,87.8,93.4
XS GIS Cut Line= 4
     1839690.468      621425.294     1839641.019      621535.782
     1839652.125      621709.787     1839526.446      621944.039
#Sta/Elev= 30
       0  773.04    55.9  769.13    74.5  767.75    93.1  766.26   102.4  765.69
   111.7  765.28   140.4   764.4   150.1  763.72   179.2  760.88   188.9  760.13
   203.8  759.34   208.2  759.14   217.9  758.99   227.6  759.28   237.3  760.05
   266.4  763.08     276  763.88   285.7  764.27   304.9   764.1   352.4  764.14
   409.3  764.56   456.8   764.7   485.3  765.15   494.8  765.39   504.3  765.82
   513.8  767.13   523.3  769.27   532.8  771.81   551.8  777.28   561.2  780.32
#Mann= 3 , 0 , 0
       0     .06       0   203.8    .045       0   227.6     .06       0
Bank Sta=203.8,227.6
XS Rating Curve= 0 ,0
Exp/Cntr=0.3,0.1

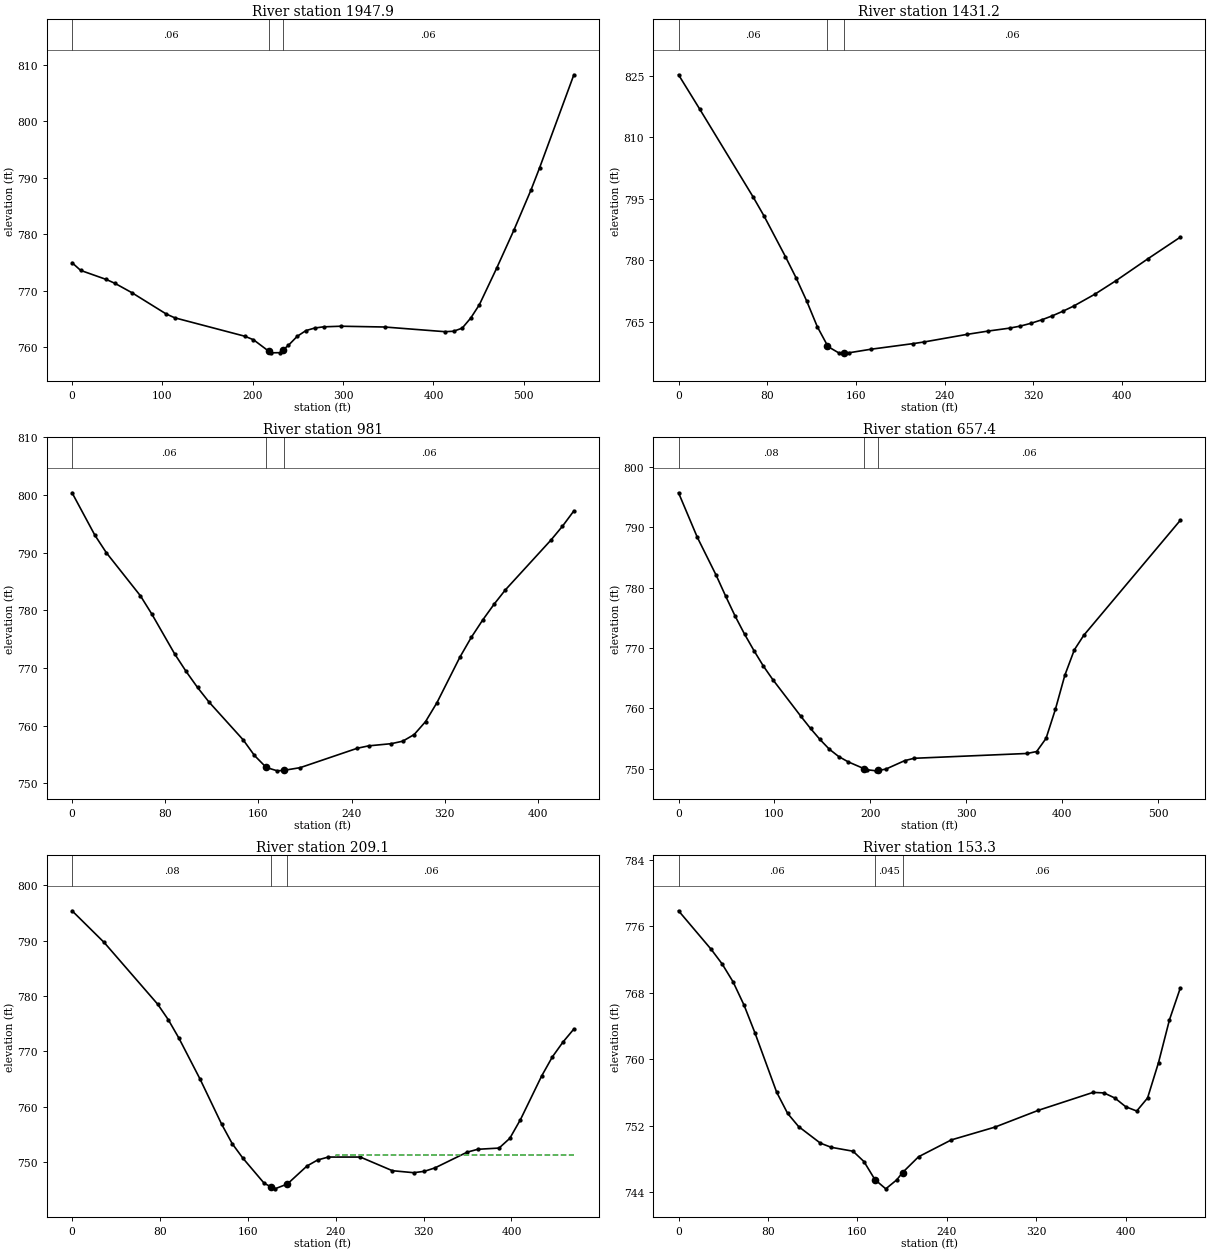
Type RM Length L Ch R = 1 ,1947.9  ,497.8,516.7,535.6
XS GIS Cut Line= 4
     1839621.236      621387.789     1839574.378      621491.355
     1839548.463         621732.      1839450.71      621906.172
#Sta/Elev= 30
       0  774.95     9.5  773.59    37.9  771.98    47.4   771.3    66.3  769.63
   104.2  765.86   113.7  765.18   191.1  761.92   200.8  761.29     218  759.22
   220.2  758.97   229.8     759     233  759.43   239.5  760.31   249.2   761.9
   258.9  762.92   268.6  763.37   278.3  763.58   297.6  763.69     346  763.55
   412.8  762.72   422.3   762.8   431.8  763.35   441.3  765.15   450.8   767.5
   469.8  773.93   488.9  780.68   507.9  787.83   517.4  791.75   555.4  808.28
#Mann= 3 , 0 , 0
       0     .06       0     218    .045       0     233     .06       0
Bank Sta=218,233
XS Rating Curve= 0 ,0
Exp/Cntr=0.3,0.1

Type RM Length L Ch R = 1 ,1431.2  ,456.3,450.3,444.3
XS GIS Cut Line= 2
        1839386.      621167.421     1839022.454      621437.418
#Sta/Elev= 29
       0  825.18    19.3  816.73    67.4  795.36    77.1  790.79    96.4  780.89
     106  775.73   115.6  770.07   125.2  763.79   134.4  759.18   134.9  758.93
   144.5  757.41   149.4  757.43   154.2  757.44   173.4  758.28     212  759.67
   221.6  760.06   260.1   761.9   279.4  762.72   298.7  763.43   308.3  763.92
     318  764.61   327.6  765.44   337.2  766.42   346.9  767.56   356.5   768.8
   375.8  771.72     395  775.04   423.9   780.4   452.8  785.61
#Mann= 3 , 0 , 0
       0     .06       0   134.4    .045       0   149.4     .06       0
Bank Sta=134.4,149.4
XS Rating Curve= 0 ,0
Exp/Cntr=0.3,0.1

Type RM Length L Ch R = 1 ,981     ,334.8,323.5,312.3
XS GIS Cut Line= 2
     1839012.802      620857.039     1838745.852      621195.138
#Sta/Elev= 30
       0  800.38    19.6  793.02    29.4     790    58.7  782.52    68.5  779.35
    88.1  772.45    97.9  769.42   107.7  766.64   117.5  764.13   146.9  757.56
   156.6  754.85   166.7  752.78   176.2  752.19   181.7  752.27   195.8  752.74
   244.8   756.1   254.6  756.52   274.1   756.9   283.9  757.33   293.7  758.48
   303.5  760.73   313.3  764.02   332.9  771.87   342.7  775.31   352.5  778.32
   362.2  781.04     372  783.55   411.2   792.2     421  794.58   430.8  797.24
#Mann= 3 , 0 , 0
       0     .06       0   166.7    .045       0   181.7     .06       0
Bank Sta=166.7,181.7
XS Rating Curve= 0 ,0
Exp/Cntr=0.3,0.1

Type RM Length L Ch R = 1 ,657.4   ,456.2,448.3,440.3
XS GIS Cut Line= 3
     1838689.588      620594.838     1838598.916      621107.636
     1838598.485      621110.072
#Sta/Elev= 30
       0  795.72    19.6  788.33    39.3  782.03    49.1   778.6      59  775.28
    68.8   772.3    78.6  769.57    88.4  767.01    98.3  764.75   127.7  758.64
   137.6  756.66   147.4  754.84   157.2  753.22     167     752   176.9  751.12
   193.4  749.99   196.5  749.81   206.3  749.63   208.4  749.69   216.2  749.92
   235.8  751.32   245.6  751.71   363.5  752.51   373.4  752.83   383.2  755.01
     393  759.86   402.8  765.48   412.7  769.69   422.5  772.09   523.2  791.16
#Mann= 3 , 0 , 0
       0     .08       0   193.4    .045       0   208.4     .06       0
Bank Sta=193.4,208.4
XS Rating Curve= 0 ,0
Exp/Cntr=0.3,0.1

Type RM Length L Ch R = 1 ,209.1   ,55.8,55.8,55.8
XS GIS Cut Line= 2
     1838193.228      620654.063      1838273.85      621103.665
#Sta/Elev= 30
       0  795.36    29.2  789.65    77.8  778.55    87.5  775.75    97.2  772.42
   116.6  764.98   136.1  756.91   145.8  753.37   155.5  750.76   174.9  746.23
     181   745.6   184.6  745.23     196   746.1   213.8  749.34   223.5  750.43
   233.2  750.96   262.4  750.96   291.6   748.5     311  748.14   320.7  748.39
   330.4  749.01   359.6  751.84   369.3  752.36   388.7  752.58   398.5  754.34
   408.2  757.72   427.6  765.62   437.3  769.04     447  771.72   456.8  774.04
#Mann= 3 , 0 , 0
       0     .08       0     181    .045       0     196     .06       0
#XS Ineff= 2 , 0
                          240.69          751.31
Permanent Ineff=
       F       F
Bank Sta=181,196
XS Rating Curve= 0 ,0
Exp/Cntr=0.3,0.1

Type RM Length L Ch R = 1 ,153.3   ,140.8,153.3,165.9
XS GIS Cut Line= 2
     1838137.787      620660.678     1838217.021      621102.543
#Sta/Elev= 30
       0  777.88    29.3  773.22      39  771.48    48.8  769.32    58.6  766.52
    68.3   763.2    87.8  756.03    97.6  753.48   107.4   751.9   126.9   749.9
   136.6   749.4   156.1  748.93   165.9  747.68   175.7  745.51   185.4   744.4
   195.2  745.48   200.4  746.36   214.7  748.26     244  750.29     283  751.83
     322  753.86   370.8  756.01   380.6  755.95   390.4  755.33   400.1  754.28
   409.9  753.77   419.6  755.34   429.4  759.61   439.2  764.76   448.9  768.59
#Mann= 3 , 0 , 0
       0     .06       0   175.7    .045       0   200.4     .06       0
Bank Sta=175.7,200.4
XS Rating Curve= 0 ,0
Exp/Cntr=0.3,0.1

Chan Stop Cuts=-1
Use User Specified Reach Order=0
Composite Channel Slope=5